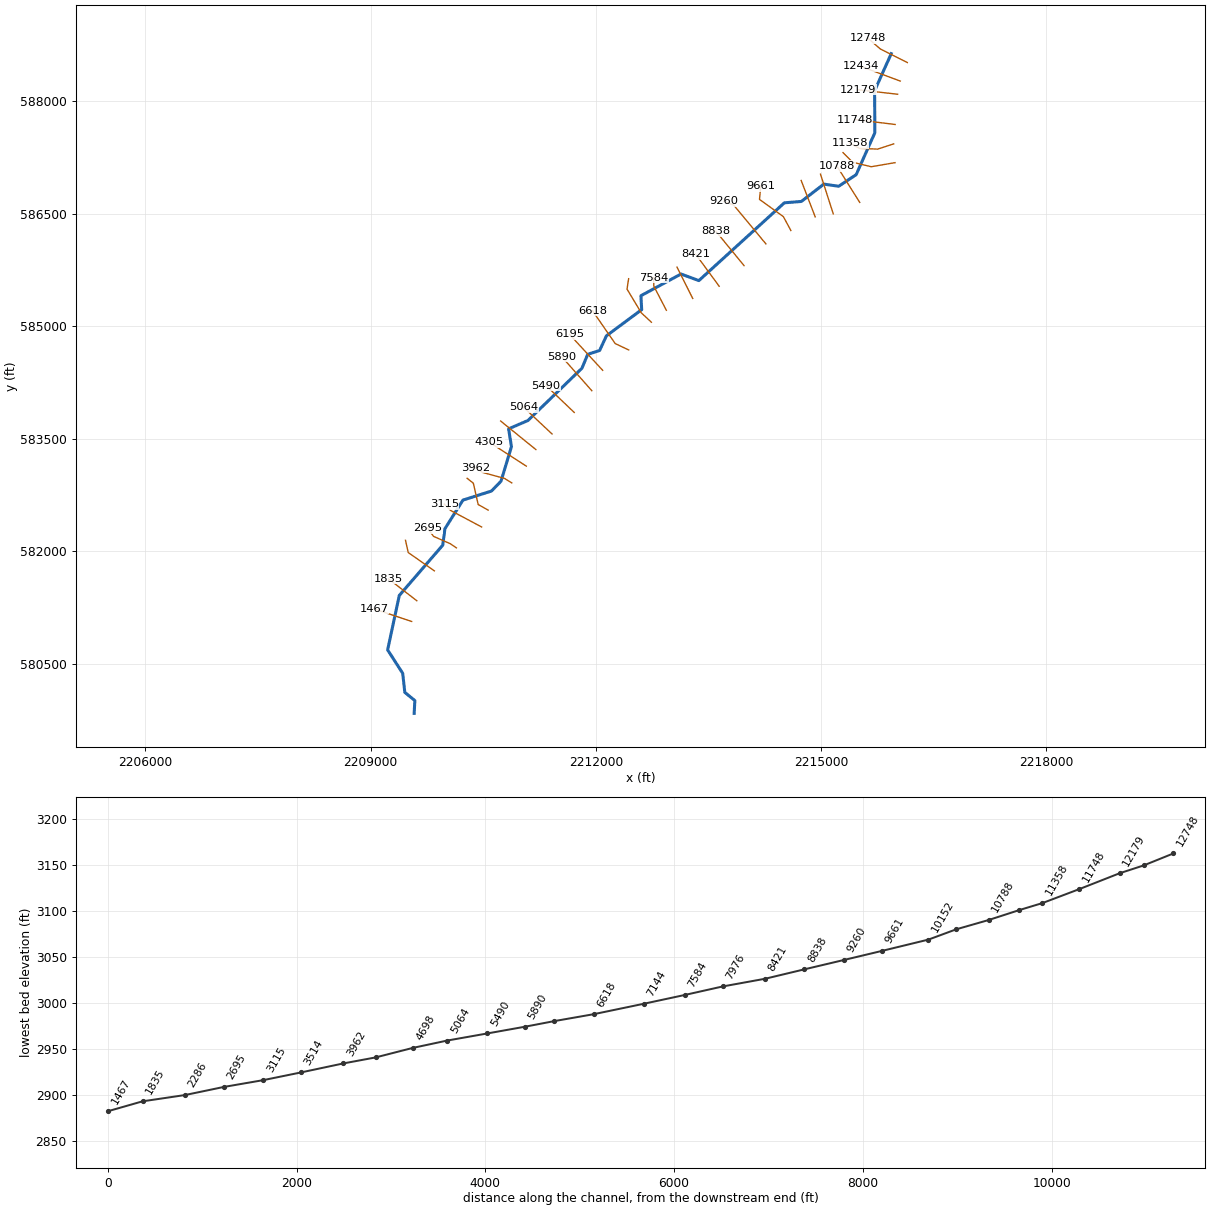
--- LFBFELKRV.prj (project) ---

Proj Title=LFBFELKRV
Current Plan=p01
Default Exp/Contr=0,0
English Units
Geom File=g01
Flow File=f01
Plan File=p01
BEGIN DESCRIPTION:
----------MODEL BY WOOD PLC 2022----------
AFH study
Randolph County, WV
HEC-RAS Version: RAS 6.2
Vertical Datum: NAVD88
Projection: NAD 1983 StatePlane West Virginia S FIPS 4702 (US Feet)
Terrain: 1-meter LIDAR (FEMA Region III 3DEP collected 2016-2018)
Land Use: 2019 NLCD
Hydrologic Method:
WV SIR2010-5033 regression equations
Additional Model Notes:
KWSEL tie-in with BFKELKRV due to main stem name change.
END DESCRIPTION:
DSS Export Rating Curves= 0
DSS Export Rating Curve Sorted= 0
DSS Export Volume Flow Curves= 0
DXF OffsetX= 0
DXF OffsetY= 0
DXF ScaleX= 0
DXF ScaleY= 0

--- LFBFELKRV.p01 (plan) ---

Plan Title=Floodplain
Program Version=6.20
Short Identifier=Floodplain
Geom File=g01
Flow File=f01
Subcritical Flow
K Sum by GR= 0
Std Step Tol= 0.01
Critical Tol= 0.01
Num of Std Step Trials= 20
Max Error Tol= 0.3
Flow Tol Ratio= 0.001
Split Flow NTrial= 30
Split Flow Tol= 0.02
Split Flow Ratio= 0.02
Log Output Level= 0
Friction Slope Method= 1
Unsteady Friction Slope Method= 2
Unsteady Bridges Friction Slope Method= 1
Parabolic Critical Depth
Global Vel Dist= 0 , 0 , 0
Global Log Level= 0
CheckData=True
Encroach Param=-1 ,0,0, 0
Mapping Interval=1HOUR
Computation Time Step Use Courant=        0
Computation Time Step Use Time Series=    0
Computation Time Step Count To Double=0
Computation Time Step Max Doubling=0
Computation Time Step Max Halving=0
Computation Time Step Residence Courant=0
Run HTab= 0
Run UNet= 0
Run Sediment= 0
Run PostProcess= 0
Run WQNet= 0
Run RASMapper=-1
UNET Theta= 0
UNET Theta Warmup= 0
UNET ZTol= 0
UNET ZSATol= 0
UNET MxIter= 0
UNET Max Iter WO Improvement= 0
UNET MaxInSteps= 0
UNET DtIC= 0
UNET DtMin= 0
UNET MaxCRTS= 0
UNET WFStab= 0
UNET SFStab= 0
UNET WFX= 1
UNET SFX= 1
UNET Gravity=32.174
UNET 1D Methodology=Finite Difference
UNET DSS MLevel= 1
UNET Pardiso=0
UNET DZMax Abort= 0
UNET Use Existing IB Tables= 0
UNET Froude Reduction=False
UNET Froude Limit= 0
UNET Froude Power= 0
UNET D1 Cores= 0
UNET WindReference=Eulerian
UNET WindDragFormulation=Hsu (1988)
UNET D2 Coriolis=0
UNET D2 Cores= 0
UNET D2 Theta= 1
UNET D2 Theta Warmup= 1
UNET D2 Z Tol= 0.01
UNET D2 Volume Tol= 0.01
UNET D2 Max Iterations= 20
UNET D2 Equation= 0
UNET D2 RampUpFraction=0.1
UNET D2 TimeSlices= 1
UNET D2 Turbulence Formulation=Non-Conservative (original)
UNET D2 Eddy Viscosity=0.3
UNET D2 Transverse Eddy Viscosity=0.1
UNET D2 Smagorinsky Mixing=0
UNET D2 BCVolumeCheck=0
UNET D2 Cores=0
UNET D2 SolverType=PARDISO (Direct)
UNET D2 Minimum Iterations= 2147483647
UNET D2 Maximum Iterations= 2147483647
UNET D2 Restart Number= 10
UNET D2 Relaxation Coeff=1.3
UNET D2 SOR Precondition Iterations= 10
UNET D2 ILUT Maximum Fill= 8
UNET D2 ILUT Tolerance=1E-08
UNET D1D2 MaxIter= 0
UNET D1D2 ZTol=0.01
UNET D1D2 QTol=0.1
UNET D1D2 MinQTol=1
Write IC File= 0
Write IC File at Fixed DateTime=0
Write IC File at Sim End=0
Echo Input=False
Echo Parameters=False
Echo Output=False
Write Detailed= 0
HDF Write Warmup=0
HDF Write Time Slices=0
HDF Flush=0
HDF Compression= 1
HDF Chunk Size= 1
HDF Spatial Parts= 1
HDF Use Max Rows=0
HDF Fixed Rows= 1
Calibration Method= 0
Calibration Iterations= 20
Calibration Max Change=0.05
Calibration Tolerance=0.2
Calibration Maximum=1.5
Calibration Minimum=0.5
Calibration Optimization Method= 1
WQ AD Non Conservative
WQ ULTIMATE=-1
WQ Max Comp Step=1HOUR
WQ Output Interval=15MIN
WQ Output Selected Increments= 0
WQ Output face flow=0
WQ Output face velocity=0
WQ Output face area=0
WQ Output face dispersion=0
WQ Output cell volume=0
WQ Output cell surface area=0
WQ Output cell continuity=0
WQ Output cumulative cell continuity=0
WQ Output face conc=0
WQ Output face dconc_dx=0
WQ Output face courant=0
WQ Output face peclet=0
WQ Output face adv mass=0
WQ Output face disp mass=0
WQ Output cell mass=0
WQ Output cell source sink temp=0
WQ Output nsm pathways=0
WQ Output nsm derived pathways=0
WQ Create Restart=0
WQ Fixed Restart=0
WQ System Summary=0
WQ Write To DSS=0
Sorting and Armoring Iterations= 10
XS Update Threshold= 0.02
Bed Roughness Predictor= 0
Hydraulics Update Threshold= 0.02
Energy Slope Method= 1
Volume Change Method= 1
Sediment Retention Method= 0
Sediment TS Multiplier= 1
Warm Up Method= 0
XS Weighting Method= 0
Number of US Weighted Cross Sections= 1
Number of DS Weighted Cross Sections= 1
Upstream XS Weight=0
Main XS Weight=1
Downstream XS Weight=0
Number of DS XS's Weighted with US Boundary= 1
Upstream Boundary Weight= 1
Weight of XSs Associated with US Boundary= 0
Number of US XS's Weighted with DS Boundary= 1
Downstream Boundary Weight= 0.5
Weight of XSs Associated with DS Boundary= 0.5
Percentile Method= 0
Sediment Output Level= 3
Mass or Volume Output= 0
Output Increment Type= 1
Profile and TS Output Increment= 1
Transport Output Increment 1
XS Output Flag= 0
XS Output Increment= 10
Read HDF5 Sediment Hotstart= 0
Sediment Hotstart Type= 0
Write Gradation File= 0
Read Gradation Hotstart= 0
Write HDF5 File= 1
Write Binary Output= 1
Write DSS Sediment File= 0
DSS Sediment Output Type= 1
SV Curve= 0
Specific Gage Flag= 0
Subcell Erosion Methods= 0
Subcell Deposition Methods= 0
Advection Scheme= 1
Matrix Solver= 0
Implicit Weighting Factor= 1
Maximum Outer Loop Convergence Iterations= 5
Convergence Maximum Absolute= 0.001
Convergence RMSE= 0.0001
Grain Fractions Max Abs Error= 0.001
Max Subgrid Regions= 1
Max Subgrid Length Scale= 3.402823E+38
Initial Layer Thickness= 3.402823E+38
Min Layer Thickness= 3.402823E+38
Max Layer Thickness= 3.402823E+38
Number of Layers= 5

--- LFBFELKRV.f01 (steady flow) ---

Flow Title=Flow
Program Version=6.20
Number of Profiles= 1
Profile Names=P100yr
River Rch & RM=LFBFELKRV,Main            ,12748
     503
River Rch & RM=LFBFELKRV,Main            ,9661
     622
River Rch & RM=LFBFELKRV,Main            ,6618
     828
River Rch & RM=LFBFELKRV,Main            ,2286
     979
River Rch & RM=LFBFELKRV,Main            ,0
    2210
Boundary for River Rch & Prof#=LFBFELKRV,Main            , 1
Up Type= 0
Dn Type= 1
Dn Known WS=2859.8
DSS Import GetInterval= 0
DSS Import GetPeak= 0
DSS Import FillOption= 0

--- LFBFELKRV.g01 (geometry) ---

Geom Title=Geometry
Program Version=6.20

River Reach=LFBFELKRV       ,Main
Reach XY= 30
2215933.95200002588631.5999999942215712.98300003588137.909000009
2215715.98800001587578.1490000042215467.02499999587018.753000021
2215233.55600001586864.4530000092215036.76200002586893.590000004
2214737.36499999586662.3620000032214510.80200003586644.133000016
2213372.03821868585607.3566289992213134.49340498585695.058633595
2212600.37400003585405.5470000062212610.48362175585220.003849775
2212141.08800003584871.7709999982212050.14000002584675.984000027
2211891.85300002584624.773000002     2211814.531584439.108999997
2211095.26574099583742.5460647792210837.94093524 583631.67182593
2210875.96500002583394.1219999942210736.78171022582933.249856681
2210609.58758253582802.320362926     2210229.689582681.641000018
     2209989.624      582299.8382209960.95563446582081.202999994
     2209381.904581410.877000004 2209226.6064574580685.039123058
2209427.48500003580372.5119999952209455.43200001580118.851000026
2209589.29799999580009.5610000042209579.97135526579839.093552321

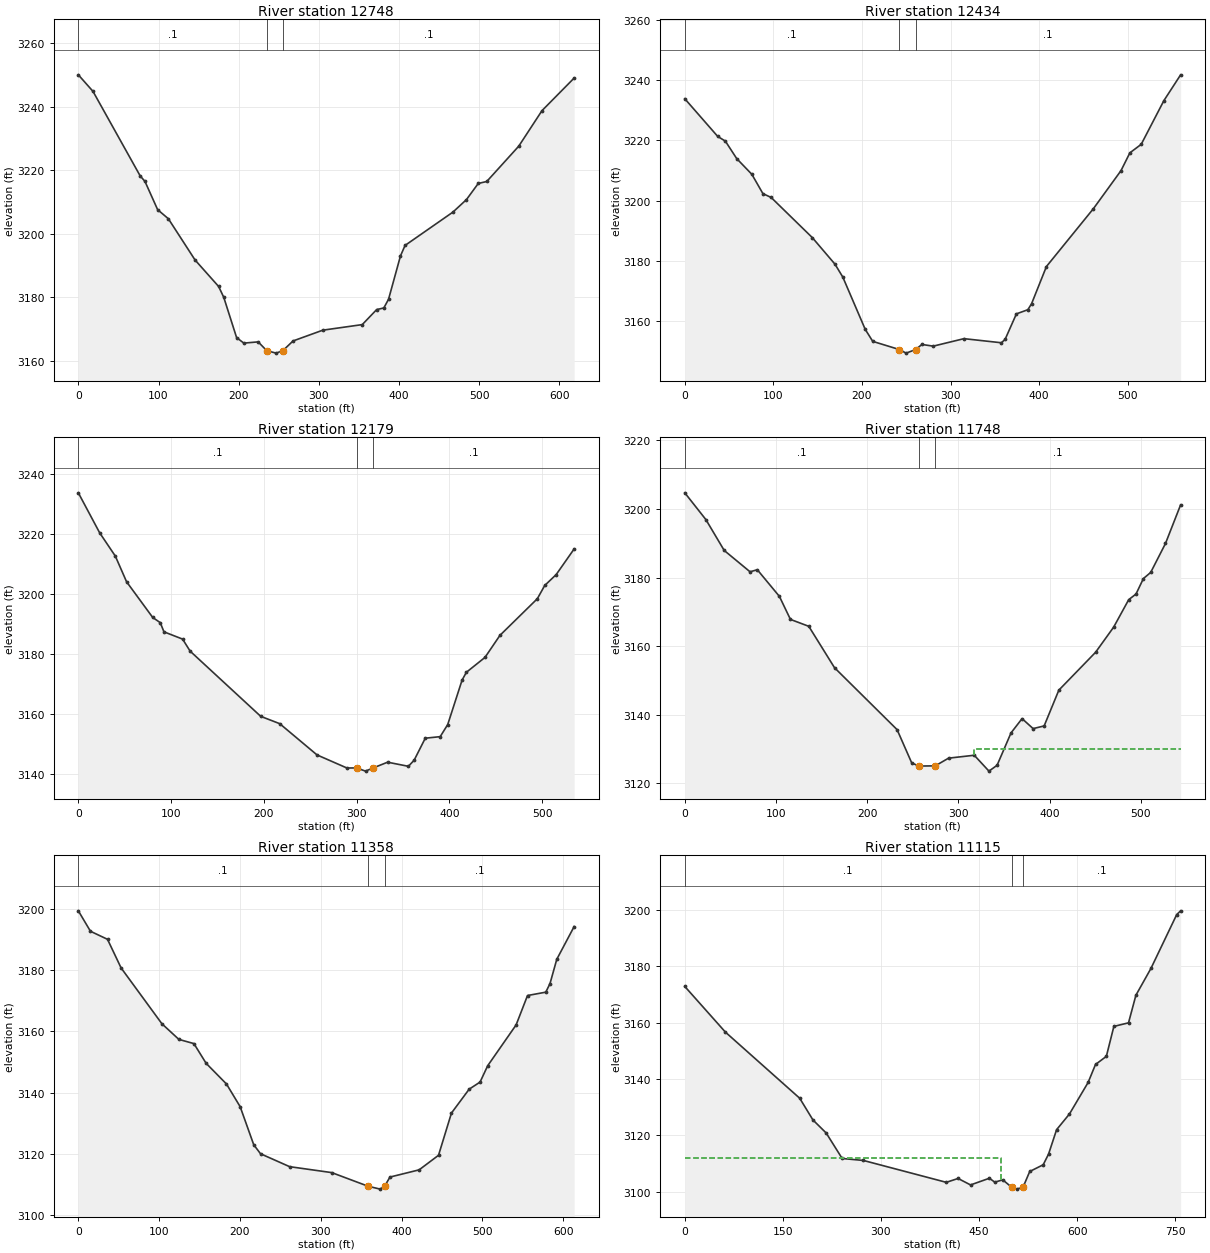
Type RM Length L Ch R = 1 ,12748   ,311.8,314,313.6
XS GIS Cut Line= 3
 2216148.4739928 588513.892343222215788.01334905588695.464563348
 2215625.9314178       588836.44
#Sta/Elev= 30
       0 3249.98    18.3 3244.77    77.1  3218.2    83.1 3216.46    98.9 3207.57
   112.3 3204.71   145.6 3191.73     175  3183.4   181.4 3179.98   197.4 3167.32
   206.4 3165.59   224.3 3165.98     235 3163.21   246.7 3162.44     255  3163.2
   267.8 3166.27   304.9 3169.66   354.1 3171.41   372.1 3176.14     381 3176.65
   386.9 3179.38   401.8 3193.03   407.5 3196.32   467.2  3206.8   484.1 3210.74
   498.8 3215.81   509.4 3216.43   549.3 3227.54   578.3 3238.72   618.4 3248.97
#Mann= 3 ,-1,0
       0      .1       0     235    .045       0     255      .1       0
Bank Sta=235,255
XS Rating Curve= 0 ,0
Exp/Cntr=0.3,0.1

Type RM Length L Ch R = 1 ,12434   ,252,255.2,256.2
XS GIS Cut Line= 2
2216055.07281474588266.6568811632215530.51465118588462.028033918
#Sta/Elev= 30
       0 3233.83    37.2 3221.32    45.8 3219.77    58.6 3213.98    75.7 3208.76
    88.2 3202.35    97.5 3201.08     144 3187.75   169.6 3178.93   178.4 3174.66
   203.7 3157.32   212.2 3153.33   242.1 3150.63   249.9 3149.43  260.513150.603
   267.7  3152.3   280.5 3151.75   315.2 3154.23   357.4 3152.87   361.6 3153.97
   374.4 3162.46   387.3 3163.83   391.5 3165.81   408.3 3178.17   461.4 3197.39
   492.5 3209.99   502.5 3215.88   515.3 3218.71   540.9 3233.21   559.8 3241.77
#Mann= 3 ,-1,0
       0      .1       0   242.1    .045       0  260.51      .1       0
Bank Sta=242.1,260.51
XS Rating Curve= 0 ,0
Exp/Cntr(USF)=0,0
Exp/Cntr=0.3,0.1

Type RM Length L Ch R = 1 ,12179   ,428.7,430.9,429.7
XS GIS Cut Line= 2
2216019.87448157588091.4954887712215488.67874799588151.229698093
#Sta/Elev= 30
       0 3233.83      23 3220.48    39.9  3212.7      52 3204.14    80.2 3192.22
    88.3  3190.5    92.3 3187.43   112.4    3185   120.5 3180.99   196.6 3159.22
   217.1 3156.77   257.3 3146.34   289.5 3141.98  299.933141.989   309.6 3140.93
   317.7 3141.98   333.4 3143.91   355.8 3142.54     362 3144.57     374 3151.92
   390.1 3152.44   398.2 3156.48   413.7 3171.33   418.3 3173.92   438.4  3178.9
   454.5 3186.25   494.8 3198.48   502.8 3202.91   515.1 3206.53   534.5 3215.11
#Mann= 3 ,-1,0
       0      .1       0  299.93    .045       0   317.7      .1       0
Bank Sta=299.93,317.7
XS Rating Curve= 0 ,0
Exp/Cntr=0.3,0.1

Type RM Length L Ch R = 1 ,11748   ,386.4,389.2,389.4
XS GIS Cut Line= 2
2215987.09171944587688.2052232312215447.69877405587754.505194068
#Sta/Elev= 30
       0 3204.71    23.1 3196.91    43.2 3187.91    71.5 3181.69    79.5 3182.28
   103.7 3174.51   115.8  3167.8   135.9 3165.79   164.1 3153.72   232.7 3135.66
   248.8 3125.92   256.8 3125.04  274.583125.097   289.1 3127.34   317.3 3128.19
   333.4 3123.56   342.3 3125.26   357.6 3134.71   369.7 3138.87   381.8 3135.96
   393.9 3136.74     410 3147.17   450.3 3158.22   470.1 3165.55   486.6 3173.56
   494.6  3175.2   502.7 3179.71   510.7  3181.5   526.9 3189.94   543.5 3201.21
#Mann= 3 ,-1,0
       0      .1       0   256.8    .045       0  274.58      .1       0
#XS Ineff= 2 , 0
                           317.3            3130
Permanent Ineff=
       F       F
Bank Sta=256.8,274.58
XS Rating Curve= 0 ,0
Exp/Cntr=0.3,0.1

Type RM Length L Ch R = 1 ,11358   ,248.6,243.6,243.4
XS GIS Cut Line= 4
2215966.48086535587429.4890000442215752.64897554587359.797640171
2215510.57608833587370.6367246732215381.16167482 587438.51635383
#Sta/Elev= 30
       0 3199.41      15 3192.73    36.1  3190.1    52.9 3180.75   103.4  3162.5
   124.4 3157.39     143 3156.02   158.1 3149.58   183.3 3142.81   200.2  3135.4
     217 3122.96   225.4 3120.02   261.4  3115.8   313.5 3113.86   358.53109.404
   373.5 3108.46     379 3109.43   385.5  3112.4   421.6 3114.76   445.6 3119.52
   461.6 3133.32   483.5 3141.12     497 3143.45   506.4 3148.77   541.6 3162.13
   555.7 3171.73   578.3 3172.83   583.5 3175.62   591.9 3183.57   613.4 3194.28
#Mann= 3 ,-1,0
       0      .1       0   358.5    .045       0     379      .1       0
Bank Sta=358.5,379
XS Rating Curve= 0 ,0
Exp/Cntr=0.3,0.1

Type RM Length L Ch R = 1 ,11115   ,330.8,326.3,316.3
XS GIS Cut Line= 4
2215985.41738575587179.5678687642215667.86632154587125.249923569
2215419.95364859587185.1389400662215291.81900865587313.273580013
#Sta/Elev= 30
       0 3172.79    62.1  3156.6   175.8 3133.13     196 3125.44   216.3  3120.8
   240.7 3111.77   273.2 3111.07     400 3103.31     418 3104.68   437.1 3102.39
   465.9 3104.76   474.1 3103.38   486.4 3104.19  499.78  3101.6   507.5  3100.9
   517.4 3101.59   527.6 3107.16   548.2 3109.54   556.4 3113.33   568.7 3121.99
   588.4 3127.57   616.9 3138.74   628.2 3145.11   644.8    3148   656.3 3158.63
   678.7 3159.89     690 3169.68     713 3179.19   752.4 3198.28   758.4 3199.62
#Mann= 3 ,-1,0
       0      .1       0  499.78    .045       0   517.4      .1       0
#XS Ineff= 2 , 0
          482.98 3111.81
Permanent Ineff=
       F       F
Bank Sta=499.78,517.4
XS Rating Curve= 0 ,0
Exp/Cntr(USF)=0,0
Exp/Cntr=0.3,0.1

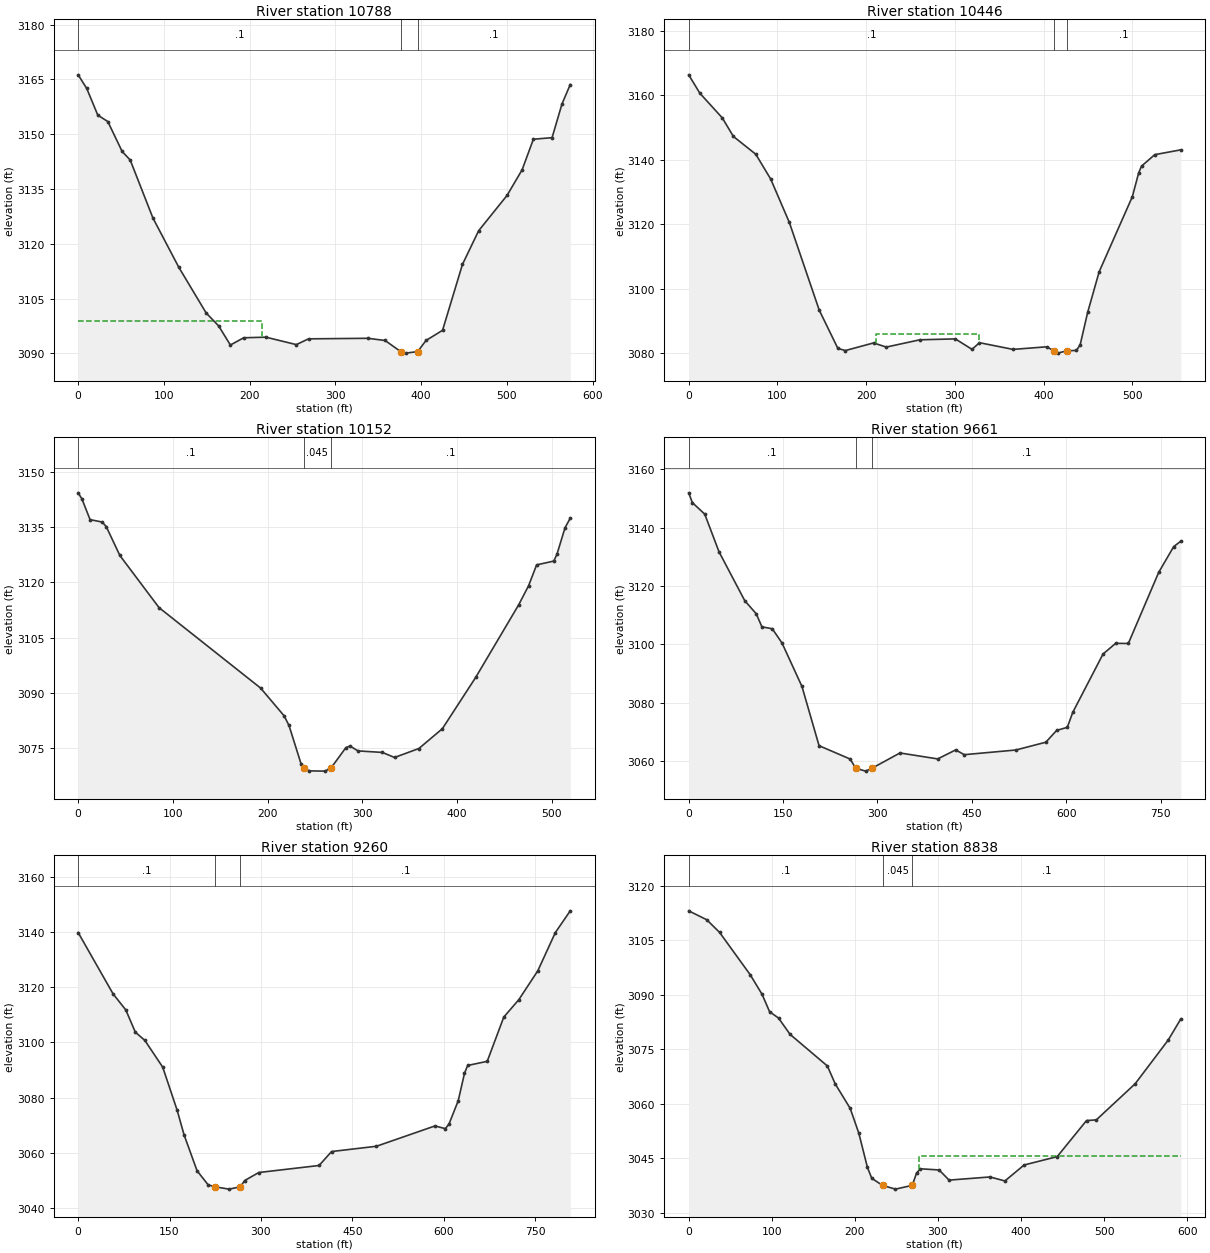
Type RM Length L Ch R = 1 ,10788   ,345.5,342.8,339.8
XS GIS Cut Line= 2
2215514.58868993586649.7466578732215209.29200496 587135.64478904
#Sta/Elev= 30
       0 3166.26      10 3162.54    22.9 3155.23    34.6 3153.46    51.3 3145.28
    60.7 3142.93    87.2 3127.05   117.4 3113.55   149.3 3101.04   163.8 3097.52
   177.5 3092.28     193 3094.26   218.9 3094.43   254.4 3092.39   268.6 3093.97
   337.9 3094.12   357.9 3093.52  376.23 3090.46     382 3090.06   395.9 3090.48
   405.6 3093.52   424.9 3096.31   448.1 3114.35     467 3123.58   500.1 3133.24
   517.7 3140.27   530.8 3148.62   552.6 3149.06   564.2 3158.32   573.8  3163.6
#Mann= 3 ,-1,0
       0      .1       0  376.23    .045       0   395.9      .1       0
#XS Ineff= 2 , 0
          214.87 3098.81
Permanent Ineff=
       F       F
Bank Sta=376.23,395.9
XS Rating Curve= 0 ,0
Exp/Cntr=0.3,0.1

Type RM Length L Ch R = 1 ,10446   ,301,294,294.9
XS GIS Cut Line= 2
2215162.22438032586497.1816139872214992.42922829587025.164535008
#Sta/Elev= 30
       0 3166.39    12.6 3160.67    37.8 3153.04    50.4 3147.25    75.6 3141.73
    92.4 3134.03   113.4 3120.57   147.1 3093.33   168.1 3081.45   176.5 3080.78
   208.3 3083.14   222.7 3081.86   260.5 3084.12   300.5  3084.4   319.3 3081.15
   327.7 3083.22   365.5 3081.14   403.4 3081.94  411.64 3080.69     416 3079.98
   425.83080.697     437 3080.82   441.2  3082.6   449.6 3092.61   462.6 3105.26
     500 3128.57   507.1 3135.94   510.3 3138.03   525.2  3141.6   554.6  3143.1
#Mann= 3 ,-1,0
       0      .1       0  411.64    .045       0   425.8      .1       0
#XS Ineff= 1 ,-1
  210.57  327.05 3085.82
Permanent Ineff=
       F
Bank Sta=411.64,425.8
XS Rating Curve= 0 ,0
Exp/Cntr(USF)=0,0
Exp/Cntr=0.3,0.1

Type RM Length L Ch R = 1 ,10152   ,478.1,490.2,494.1
XS GIS Cut Line= 2
2214921.35583583586457.4383041462214734.76159163 586942.28760554
#Sta/Elev= 30
       0 3144.27       4 3142.61    12.6    3137    25.4 3136.35    29.7  3135.1
      44  3127.3    85.4 3113.15   192.6 3091.35   217.4 3083.83   222.6  3081.2
   235.5 3070.66     238 3069.76     244  3068.9   260.7 3068.83  267.173069.761
   282.6 3075.18   286.9 3075.63   295.5 3074.31   321.2  3073.9     334 3072.53
   359.7 3074.96   384.5 3080.33   419.7 3094.25     465 3113.89   475.5 3119.08
     484 3124.74   502.1 3125.77   505.5 3127.64     514 3134.82   519.5  3137.4
#Mann= 3 ,-1,0
       0      .1       0     238    .045       0  267.17      .1       0
Bank Sta=238,267.17
XS Rating Curve= 0 ,0
Exp/Cntr=0.3,0.1

Type RM Length L Ch R = 1 ,9661    ,404.4,401.8,400.9
XS GIS Cut Line= 4
2214597.63636158586274.7669905722214497.91953989586459.670727754
2214179.48071879 586689.876449582214197.53718774586868.125338009
#Sta/Elev= 30
       0 3151.88     5.8 3148.53    25.5 3144.58    48.2 3131.69    89.1 3114.95
   107.3 3110.49   116.4 3105.99   132.8 3105.35   148.2 3100.52     180  3085.6
   207.2 3065.31   256.7 3060.73  265.373057.604   281.2  3056.6   291.2 3057.57
   335.8 3062.82   395.8 3060.78   424.4 3063.87     438 3062.23   519.9 3063.83
   567.7  3066.5   584.8 3070.54   601.8 3071.59   610.4  3076.7   658.6  3096.7
   678.7 3100.35   698.8  3100.3     747 3124.62   770.9 3133.47   782.2 3135.31
#Mann= 3 ,-1,0
       0      .1       0  265.37    .045       0   291.2      .1       0
Bank Sta=265.37,291.2
XS Rating Curve= 0 ,0
Exp/Cntr=0.3,0.1

Type RM Length L Ch R = 1 ,9260    ,418.9,422,419
XS GIS Cut Line= 3
2214264.75521603586096.9280093112213835.03870017586615.207200788
2213709.20423477586662.943732352
#Sta/Elev= 30
       0 3139.89    57.4  3117.6    78.3 3111.77    93.9 3103.71   109.4 3100.77
   138.8 3091.04   162.5  3075.4   173.9 3066.44   195.2 3053.42   213.4 3048.32
  224.593047.598   247.7 3046.76  266.183047.597   273.3 3049.87   296.5 3052.79
   395.5 3055.34     416  3060.4   489.7 3062.32   585.8  3069.7   602.8  3068.7
   608.8 3070.41   623.9 3078.82   634.2 3088.81   639.4 3091.64   671.5 3093.14
   698.7  3109.2   723.4 3115.53   754.5 3125.98   783.3 3139.86   807.8 3147.76
#Mann= 3 ,-1,0
       0      .1       0  224.59    .045       0  266.18      .1       0
Bank Sta=224.59,266.18
XS Rating Curve= 0 ,0
Exp/Cntr=0.3,0.1

Type RM Length L Ch R = 1 ,8838    ,417.6,417.1,415.9
XS GIS Cut Line= 2
2213973.91657749585806.7604599892213598.59746942586265.004201886
#Sta/Elev= 30
       0 3113.09    21.7 3110.64    37.1 3107.18      74 3095.52    88.2 3090.17
    97.4 3085.32   108.1  3083.6     122 3079.11   166.9 3070.41   176.3  3065.5
   194.4 3058.73   204.8 3051.88   215.1 3042.53   220.3 3039.52   233.4 3037.54
   248.9 3036.53  269.143037.574   274.2 3040.93   278.7 3042.13   301.4  3041.8
   313.4 3039.01   362.6 3039.88   380.6 3038.78   403.7 3043.17   443.5 3045.47
   478.8 3055.39   490.6 3055.58   537.3  3065.5   577.1 3077.53   592.3 3083.35
#Mann= 3 ,-1,0
       0      .1       0   233.4    .045       0  269.14      .1       0
#XS Ineff= 2 , 0
                          277.69         3045.74
Permanent Ineff=
       F       F
Bank Sta=233.4,269.14
XS Rating Curve= 0 ,0
Exp/Cntr=0.3,0.1

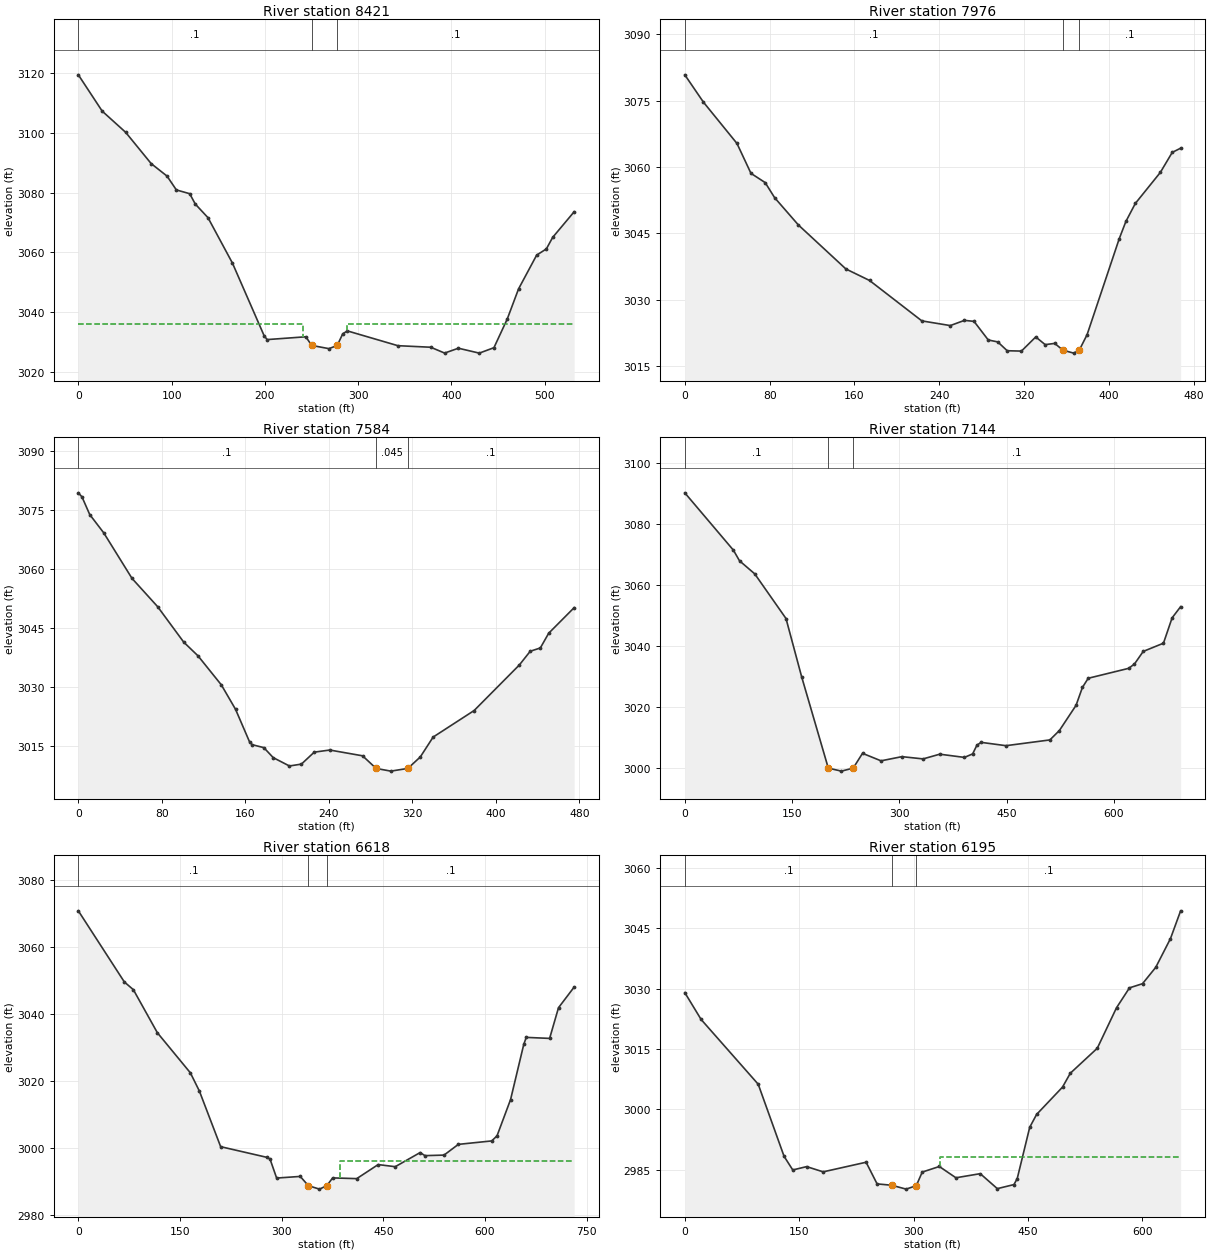
Type RM Length L Ch R = 1 ,8421    ,453.6,450.1,443.3
XS GIS Cut Line= 2
2213642.34386458585532.5030932992213328.01041402585961.249102494
#Sta/Elev= 30
       0 3119.39    25.6 3107.24    50.7 3100.17    78.1 3089.69    95.1 3085.51
   105.1 3080.88   119.4 3079.62   125.4 3076.15     139  3071.6   165.2 3056.42
   199.2 3032.11   202.4 3030.81   243.9 3031.75  250.213028.855   268.7 3027.78
  277.623028.856   283.5 3032.76   288.5 3033.71   342.6 3028.77   377.8 3028.25
   392.7  3026.3   407.5 3027.92   429.9 3026.28   445.6  3028.1   459.9 3037.72
     472 3047.78   491.4 3059.07   501.8 3061.15   508.6 3065.02   531.6 3073.58
#Mann= 3 ,-1,0
       0      .1       0  250.21    .045       0  277.62      .1       0
#XS Ineff= 2 , 0
          240.89 3036.14   288.2            3036
Permanent Ineff=
       F       F
Bank Sta=250.21,277.62
XS Rating Curve= 0 ,0
Exp/Cntr(USF)=0,0
Exp/Cntr=0.3,0.1

Type RM Length L Ch R = 1 ,7976    ,398.1,398.4,396.8
XS GIS Cut Line= 2
 2213290.2302442585369.4248355932213080.61347695585787.345353402
#Sta/Elev= 30
       0 3080.83    17.6 3074.64    49.2 3065.31    62.4 3058.55    75.8 3056.46
    84.7 3053.05   107.1 3046.88   151.9 3036.93   174.2 3034.33   223.5 3025.19
   250.3 3024.13   263.7 3025.31   272.7 3025.08   286.1 3020.88   295.1 3020.43
     304 3018.44   317.4 3018.36   330.9 3021.56   339.8 3019.82   348.8  3020.1
  356.59 3018.56   366.7  3017.9   371.9 3018.55   379.3 3022.07   409.6 3043.76
   415.9 3047.68   424.8 3051.75   448.4 3058.77   459.6 3063.29   467.5 3064.24
#Mann= 3 ,-1,0
       0      .1       0  356.59    .045       0   371.9      .1       0
Bank Sta=356.59,371.9
XS Rating Curve= 0 ,0
Exp/Cntr=0.3,0.1

Type RM Length L Ch R = 1 ,7584    ,436,439.9,434.3
XS GIS Cut Line= 3
2212939.20856346585211.523507013 2212771.7972442585533.778145551
2212769.76761968585645.626263051
#Sta/Elev= 30
       0 3079.43     3.5  3078.4    10.9 3073.92    24.4 3069.24    51.4  3057.7
      76  3050.5     101 3041.49   114.6 3038.03     137 3030.64   150.6 3024.44
   164.1 3016.12   166.6 3015.44   177.7  3014.7   186.7 3012.16   202.2 3010.04
   213.7 3010.51     226 3013.55   240.9 3014.09   272.3 3012.62   285.3 3009.41
   299.4 3008.73   315.7 3009.42   327.6 3012.33   339.9 3017.38   379.2 3024.13
   422.6 3035.73   432.9 3039.18   442.6 3040.02   450.6 3043.76     475 3050.26
#Mann= 3 ,-1,0
       0      .1       0   285.3    .045       0   315.7      .1       0
Bank Sta=285.3,315.7
XS Rating Curve= 0 ,0
Exp/Cntr=0.3,0.1

Type RM Length L Ch R = 1 ,7144    ,524.6,526,527.3
XS GIS Cut Line= 4
 2212739.6602865585052.4900563352212604.67074178585178.465352151
 2212415.1186304585493.964126181  2212436.646967585632.860093814
#Sta/Elev= 30
       0 3090.37      68 3071.54    76.5 3068.07    97.8 3063.78   141.5 3049.13
   163.4 3029.99  200.643000.035     219 2999.05  235.443000.034   248.5 3004.89
   274.4 3002.43   303.6  3003.8   333.2 3003.06   356.5 3004.61     391 3003.55
   402.5 3004.71   408.5 3007.58   414.4 3008.49   449.1  3007.4   510.5 3009.29
   523.8 3012.38   547.1 3020.65     556 3026.53   564.1 3029.52   620.7 3032.78
   628.8 3034.22     641 3038.33   669.3 3041.03   681.4 3049.35   693.3 3053.01
#Mann= 3 ,-1,0
       0      .1       0  200.64    .045       0  235.44      .1       0
Bank Sta=200.64,235.44
XS Rating Curve= 0 ,0
Exp/Cntr=0.3,0.1

Type RM Length L Ch R = 1 ,6618    ,420.6,423.2,424.3
XS GIS Cut Line= 3
2212437.52421131584682.8997323522212257.64248356584768.177018856
2211955.05960566585206.394727754
#Sta/Elev= 30
       0 3070.83    67.9 3049.61    81.2 3047.31   116.6 3034.47   165.3 3022.51
   178.6 3017.08     210 3000.48   279.1 2997.26   282.9 2996.76   292.6 2991.12
   327.4 2991.61  339.482988.843   355.8 2987.82  366.552988.842   375.3 2991.17
   410.8 2990.95   442.4 2995.14   467.6 2994.51   504.4 2998.73   511.4 2997.81
   539.6 2997.97   560.7 3001.17     610  3002.2   617.8 3003.72   637.8 3014.55
   657.2 3030.96   660.9 3033.08   695.4 3032.78   708.5 3041.93   731.6 3048.09
#Mann= 3 ,-1,0
       0      .1       0  339.48    .045       0  366.55      .1       0
#XS Ineff= 2 , 0
                          385.85         2996.12
Permanent Ineff=
       F       F
Bank Sta=339.48,366.55
XS Rating Curve= 0 ,0
Exp/Cntr=0.3,0.1

Type RM Length L Ch R = 1 ,6195    ,301,305,304
XS GIS Cut Line= 2
2212090.67350242584411.6528403072211650.10398926584889.984491302
#Sta/Elev= 30
       0 3029.01    21.4 3022.34    96.3 3006.25   130.2 2988.35   141.6 2984.96
   159.8 2985.79   181.5 2984.49   237.8 2986.88   252.2  2981.5   271.42981.165
   290.3  2980.2   303.62981.063   311.4 2984.43   333.8 2985.82   355.6 2983.02
   387.5 2984.04   409.9 2980.32   431.7 2981.33     436 2982.82   452.4 2995.57
   461.4 2998.75   495.4 3005.54   505.6 3008.98     541 3015.19   566.2 3025.24
   583.2 3030.19   600.3 3031.22   617.7 3035.29     637 3042.43   650.3 3049.32
#Mann= 3 ,-1,0
       0      .1       0   271.4    .045       0   303.6      .1       0
#XS Ineff= 2 , 0
                          335.16         2988.27
Permanent Ineff=
       F       F
Bank Sta=271.4,303.6
XS Rating Curve= 0 ,0
Exp/Cntr=0.3,0.1

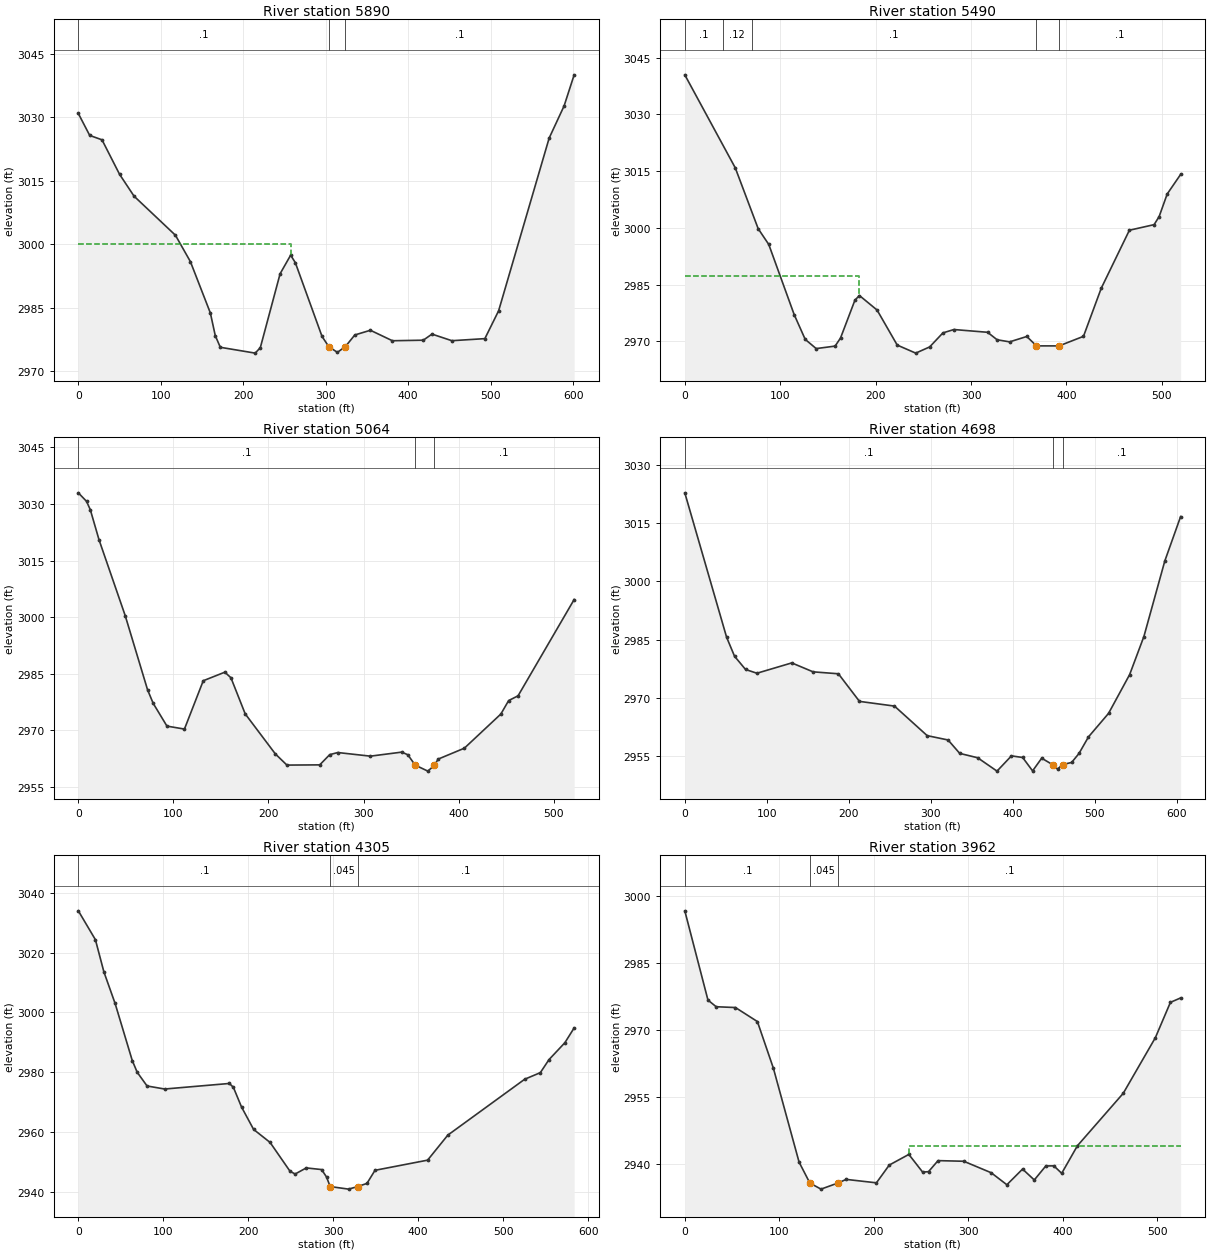
Type RM Length L Ch R = 1 ,5890    ,398.7,399.6,400.7
XS GIS Cut Line= 2
2211946.14236618584139.6948308792211548.11297172 584590.33937089
#Sta/Elev= 30
       0 3030.93    13.8 3025.74    28.7  3024.7      50 3016.54    67.6 3011.36
   117.8 3002.11   135.9 2995.88   160.1 2983.73   166.1 2978.34   172.2  2975.6
   214.5 2974.22   220.7 2975.51   244.7 2993.01   257.5 2997.41   263.2 2995.61
   295.5 2978.19  303.73 2975.74   314.2  2974.4  323.882975.772   335.3 2978.52
   354.2 2979.63   380.9 2977.15   418.3 2977.28   428.9 2978.72     453 2977.16
     493 2977.65   509.7 2984.24     571 3025.12   589.1 3032.72   601.3 3040.08
#Mann= 3 ,-1,0
       0      .1       0  303.73    .045       0  323.88      .1       0
#XS Ineff= 2 , 0
           257.5    3000
Permanent Ineff=
       F       F
Bank Sta=303.73,323.88
XS Rating Curve= 0 ,0
Exp/Cntr=0.3,0.1

Type RM Length L Ch R = 1 ,5490    ,424.2,425.5,424.3
XS GIS Cut Line= 2
2211711.78248048583850.0363100282211336.02755108 584208.93044132
#Sta/Elev= 30
       0 3040.47    52.9 3015.87    76.9 2999.79      88 2995.62   114.6 2977.09
   126.2 2970.52   137.7 2968.09   157.5 2968.75   163.2 2970.89   178.3  2980.9
     183 2982.12   201.5 2978.28   222.6 2969.02     242 2966.89   256.6 2968.53
   270.5 2972.24     282 2973.13   317.3  2972.4   327.3 2970.42   340.4 2969.87
   358.4 2971.29  368.522968.806   392.2  2968.8   417.8 2971.33   436.4 2984.04
   465.9 2999.38   491.8 3000.86   497.1    3003   505.5 3008.95   519.6 3014.14
#Mann= 5 ,-1,0
       0      .1       0      40     .12       0      70      .1       0
  368.52    .045       0   392.2      .1       0
#XS Ineff= 2 , 0
           182.9 2987.22
Permanent Ineff=
       F       F
Bank Sta=368.52,392.2
XS Rating Curve= 0 ,0
Exp/Cntr(USF)=0,0
Exp/Cntr=0.3,0.1

Type RM Length L Ch R = 1 ,5064    ,365.9,366.8,364.1
XS GIS Cut Line= 2
2211416.07215969583563.3057136122211035.95361497  583920.3891175
#Sta/Elev= 30
       0 3032.96     8.6 3030.71    12.6 3028.48    21.8 3020.48    49.3  3000.4
    72.8 2980.74    78.7 2977.15    93.2  2971.1   111.6 2970.31   131.4 2983.13
   154.1  2985.4   160.5 2983.92   175.5 2974.35   207.2 2963.73   219.4 2960.76
   253.9 2960.82   264.4 2963.53   272.9 2964.09   307.2 2963.13   340.1  2964.2
   346.5 2963.51  354.322960.752   367.6 2959.16   374.42960.682   378.5 2962.35
     406 2965.24   444.4  2974.3   452.6 2977.87   462.5 2979.13   521.5 3004.67
#Mann= 3 ,-1,0
       0      .1       0  354.32    .045       0   374.4      .1       0
Bank Sta=354.32,374.4
XS Rating Curve= 0 ,0
Exp/Cntr=0.3,0.1

Type RM Length L Ch R = 1 ,4698    ,394.3,392.6,382.4
XS GIS Cut Line= 2
2211201.70069959 583354.954629112210731.85277454583735.956248909
#Sta/Elev= 30
       0  3022.8      51 2985.61    60.7 2980.71    74.1 2977.31      88 2976.34
   130.5    2979   156.5  2976.7   187.4  2976.2   213.1 2969.09   255.8 2967.88
   295.7 2960.27   321.2 2959.15   335.4  2955.7   357.3 2954.57   380.9 2951.13
   398.5 2955.06   412.2 2954.64   424.3 2951.19   435.4 2954.46  448.612952.812
   454.8 2951.66   460.8 2952.82   471.9 2953.36   480.9 2955.67   492.5 2959.95
     517 2966.01   542.7 2975.99   560.1  2985.8   585.6 3005.25   604.9 3016.69
#Mann= 3 ,-1,0
       0      .1       0  448.61    .045       0   460.8      .1       0
Bank Sta=448.61,460.8
XS Rating Curve= 0 ,0
Exp/Cntr=0.3,0.1

Type RM Length L Ch R = 1 ,4305    ,335.8,343.3,344.6
XS GIS Cut Line= 2
2211073.48083758583134.6567328892210583.31334954583451.398868895
#Sta/Elev= 30
       0 3033.99    20.1 3024.33    30.1 3013.54    43.3 3002.97    63.5 2983.86
    69.3 2979.94    80.9 2975.36   101.6 2974.34   177.8  2976.2   182.5 2974.91
   192.1 2968.31   206.3 2960.82   225.7 2956.46   249.2  2946.8   255.2 2945.89
   268.3 2947.93   286.3 2947.38   292.1 2944.91  296.432941.686   318.1 2940.83
   328.72941.686   339.7 2942.74   349.2 2947.13   411.1 2950.53   434.9 2958.91
   525.4 2977.62   543.8 2979.82     554 2984.19   572.7 2989.85   583.6  2994.8
#Mann= 3 ,-1,0
       0      .1       0  296.43    .045       0   328.7      .1       0
Bank Sta=296.43,328.7
XS Rating Curve= 0 ,0
Exp/Cntr(USF)=0,0
Exp/Cntr=0.3,0.1

Type RM Length L Ch R = 1 ,3962    ,460.2,447.7,427.8
XS GIS Cut Line= 4
2210879.91900954582911.1677606362210783.23424147582970.866122635
2210485.42508933 583052.004558752210403.51953518583113.213108072
#Sta/Elev= 30
       0 2996.58    24.5  2976.6    33.2 2975.11    53.6 2974.93    76.8 2971.79
    93.7 2961.35   120.9 2940.32  132.292935.641   144.1 2934.28   162.4 2935.68
   170.7 2936.46   202.7 2935.69   216.3 2939.67     237 2942.05   251.6 2938.09
   257.8 2938.19   267.9 2940.66   295.1 2940.52   324.1 2937.95   340.7 2935.26
   357.3 2938.77   369.7 2936.33   381.9 2939.47   390.4 2939.49   398.7 2937.82
   415.3 2943.98   463.8 2955.73   497.8 2968.19   513.7 2976.09   524.5 2977.08
#Mann= 3 ,-1,0
       0      .1       0  132.29    .045       0   162.4      .1       0
#XS Ineff= 2 , 0
                             237            2944
Permanent Ineff=
       F       F
Bank Sta=132.29,162.4
XS Rating Curve= 0 ,0
Exp/Cntr=0.3,0.1

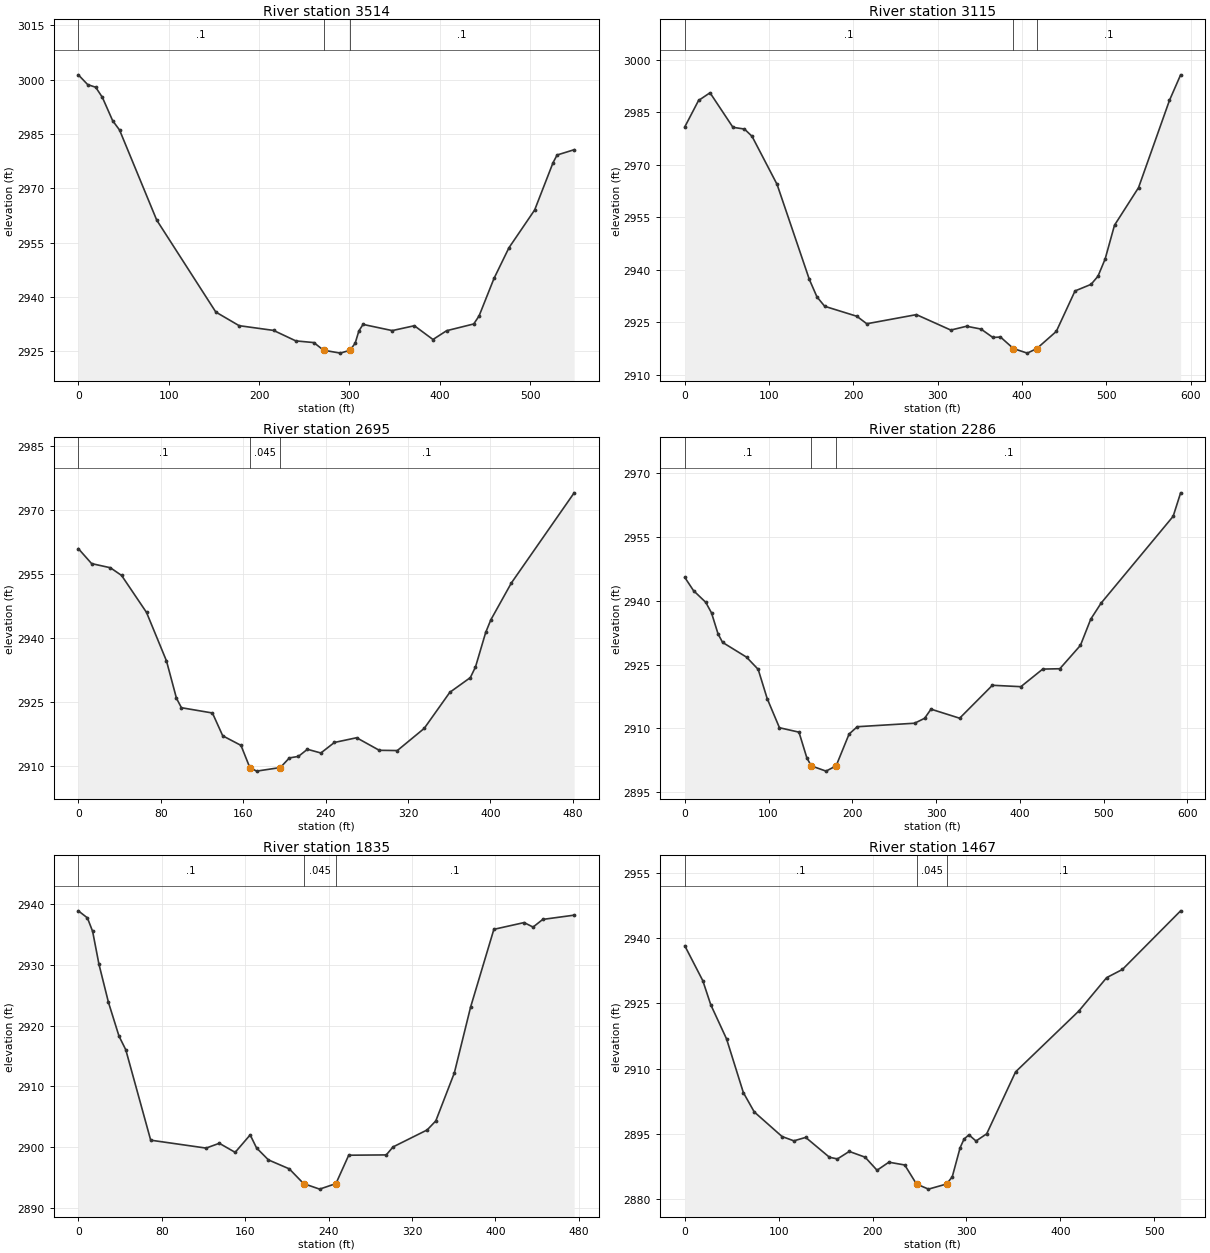
Type RM Length L Ch R = 1 ,3514    ,381,398.7,406.7
XS GIS Cut Line= 4
 2210565.2482087582548.1418270532210432.77050923582622.811075845
2210368.25319257582906.7986431362210285.94551173582972.424910901
#Sta/Elev= 30
       0 3001.33    10.4 2998.62    19.2 2997.91    26.6 2995.11      38 2988.66
    45.6  2986.1    86.7 2961.25   152.1 2935.86   177.9  2932.1     216 2930.79
   240.6  2927.9   260.6 2927.43  271.282925.329   289.9 2924.52  300.67 2925.33
   306.3 2927.26   310.4 2930.64     315 2932.45   347.3 2930.74   371.8 2932.08
   392.4 2928.28   407.5 2930.71   437.5 2932.57   443.4 2934.79   459.9 2945.13
   476.4 2953.58   504.9 2964.03   525.2 2977.06   529.7  2979.2   548.6 2980.66
#Mann= 3 ,-1,0
       0      .1       0  271.28    .045       0  300.67      .1       0
Bank Sta=271.28,300.67
XS Rating Curve= 0 ,0
Exp/Cntr=0.3,0.1

Type RM Length L Ch R = 1 ,3115    ,418.5,420.7,420.9
XS GIS Cut Line= 3
2210478.54051644582323.5708215682210064.65806576582544.125488273
 2209981.1522581582628.749615085
#Sta/Elev= 30
       0 2980.82    16.3 2988.36    29.9 2990.56    57.1 2980.69    70.7  2980.2
    79.7 2978.13   109.4 2964.39   147.7 2937.21   156.7 2932.24   165.9 2929.55
     204  2926.7   215.8 2924.56   274.6 2927.17   315.4 2922.76   334.1 2923.85
   351.2 2923.05   365.3 2920.64   374.3 2920.77  389.732917.461   406.1 2916.17
  417.332917.461   440.5 2922.38   462.7 2933.94   481.7 2935.82   489.9 2938.14
   498.4 2943.07   509.5 2952.72     538 2963.46   574.7 2988.41   587.9 2995.69
#Mann= 3 ,-1,0
       0      .1       0  389.73    .045       0  417.33      .1       0
Bank Sta=389.73,417.33
XS Rating Curve= 0 ,0
Exp/Cntr=0.3,0.1

Type RM Length L Ch R = 1 ,2695    ,411.9,409.1,406.1
XS GIS Cut Line= 4
2210142.86568085582044.6216384222210059.77167602582101.371230053
2209839.02954706582197.6780948182209755.90780271 582310.31074178
#Sta/Elev= 30
       0 2960.97    12.9 2957.45    31.1 2956.48      42 2954.67    66.2 2945.99
    85.6 2934.59    95.3 2925.81   100.1 2923.61   130.2 2922.37   140.2 2917.01
   157.9 2914.77  166.492909.564   173.1 2908.72  196.122909.562   204.9 2911.82
   213.7 2912.18   222.4 2913.85   235.5 2912.98   248.6 2915.45   270.2 2916.56
   292.2 2913.61   309.7 2913.55   335.8 2918.75   360.7 2927.23   380.6 2930.68
   385.6 2933.18   395.5 2941.28   400.5 2944.25   420.4 2952.89   481.4 2974.07
#Mann= 3 ,-1,0
       0      .1       0  166.49    .045       0  196.12      .1       0
Bank Sta=166.49,196.12
XS Rating Curve= 0 ,0
Exp/Cntr=0.3,0.1

Type RM Length L Ch R = 1 ,2286    ,451.5,450.7,450
XS GIS Cut Line= 3
2209848.66428884581738.8235175622209500.60924205581983.305090221
2209464.47896038582145.891357753
#Sta/Elev= 30
       0 2945.54    10.4 2942.43      25 2939.68    31.9 2937.19    39.7 2932.24
    45.1 2930.25    73.7 2926.78    87.6  2923.9    98.4    2917     113 2910.17
   136.3 2909.13   145.6 2903.14  150.852901.208   168.6 2899.96  180.662901.206
   196.1 2908.68   205.9 2910.41   274.3 2911.23   286.3 2912.39   293.9 2914.54
   328.1 2912.41   367.2 2920.16   401.2 2919.83   427.3 2923.97   447.7 2924.05
   472.3 2929.55   484.6 2935.72   496.9 2939.47     583 2959.92   591.9 2965.44
#Mann= 3 ,-1,0
       0      .1       0  150.85    .045       0  180.66      .1       0
Bank Sta=150.85,180.66
XS Rating Curve= 0 ,0
Exp/Cntr(USF)=0,0
Exp/Cntr=0.3,0.1

Type RM Length L Ch R = 1 ,1835    ,362,367.4,371.9
XS GIS Cut Line= 2
2209615.02180069581340.1860764292209239.26687128581631.637015264
#Sta/Elev= 30
       0 2938.84     8.7 2937.68    13.7 2935.47    19.8 2930.05    28.9  2923.8
      39 2918.26    45.5 2916.02    69.4 2901.17   122.5 2899.87   135.2 2900.66
   150.4 2899.17   164.8 2902.04   170.9  2899.9   182.3 2897.93   202.3 2896.46
  216.022894.037   231.4 2893.13  247.042894.038   259.3  2898.7   295.3 2898.75
   301.8 2900.06   334.5 2902.85   342.8 2904.33   360.6 2912.22   376.2 2923.04
   398.5  2935.8   427.5 2936.91   436.1 2936.17   445.4 2937.43   475.5 2938.13
#Mann= 3 ,-1,0
       0      .1       0  216.02    .045       0  247.04      .1       0
Bank Sta=216.02,247.04
XS Rating Curve= 0 ,0
Exp/Cntr(USF)=0,0
Exp/Cntr=0.3,0.1

Type RM Length L Ch R = 1 ,1467    ,422.8,432.4,438.4
XS GIS Cut Line= 2
2209546.37426551581064.3915929872209045.36769296581231.795231408
#Sta/Elev= 30
       0  2938.2    19.2 2930.18    27.6  2924.7    44.5 2916.82    62.4  2904.5
      74 2900.07   103.6 2894.43   116.2 2893.44   128.8 2894.23   154.1 2889.67
   162.6 2889.29   175.2 2891.01   192.1 2889.69   204.8 2886.69   217.4 2888.54
   234.3  2887.9  246.832883.532   259.6 2882.36   278.82883.533   284.9 2885.17
   293.3 2891.87   297.5 2893.85   302.7 2894.82   310.2  2893.4   321.6 2895.05
   352.4 2909.27   419.8 2923.24   449.4 2930.89   466.2 2932.77   528.2 2946.22
#Mann= 3 ,-1,0
       0      .1       0  246.83    .045       0   278.8      .1       0
Bank Sta=246.83,278.8
XS Rating Curve= 0 ,0
Exp/Cntr(USF)=0,0
Exp/Cntr=0.3,0.1