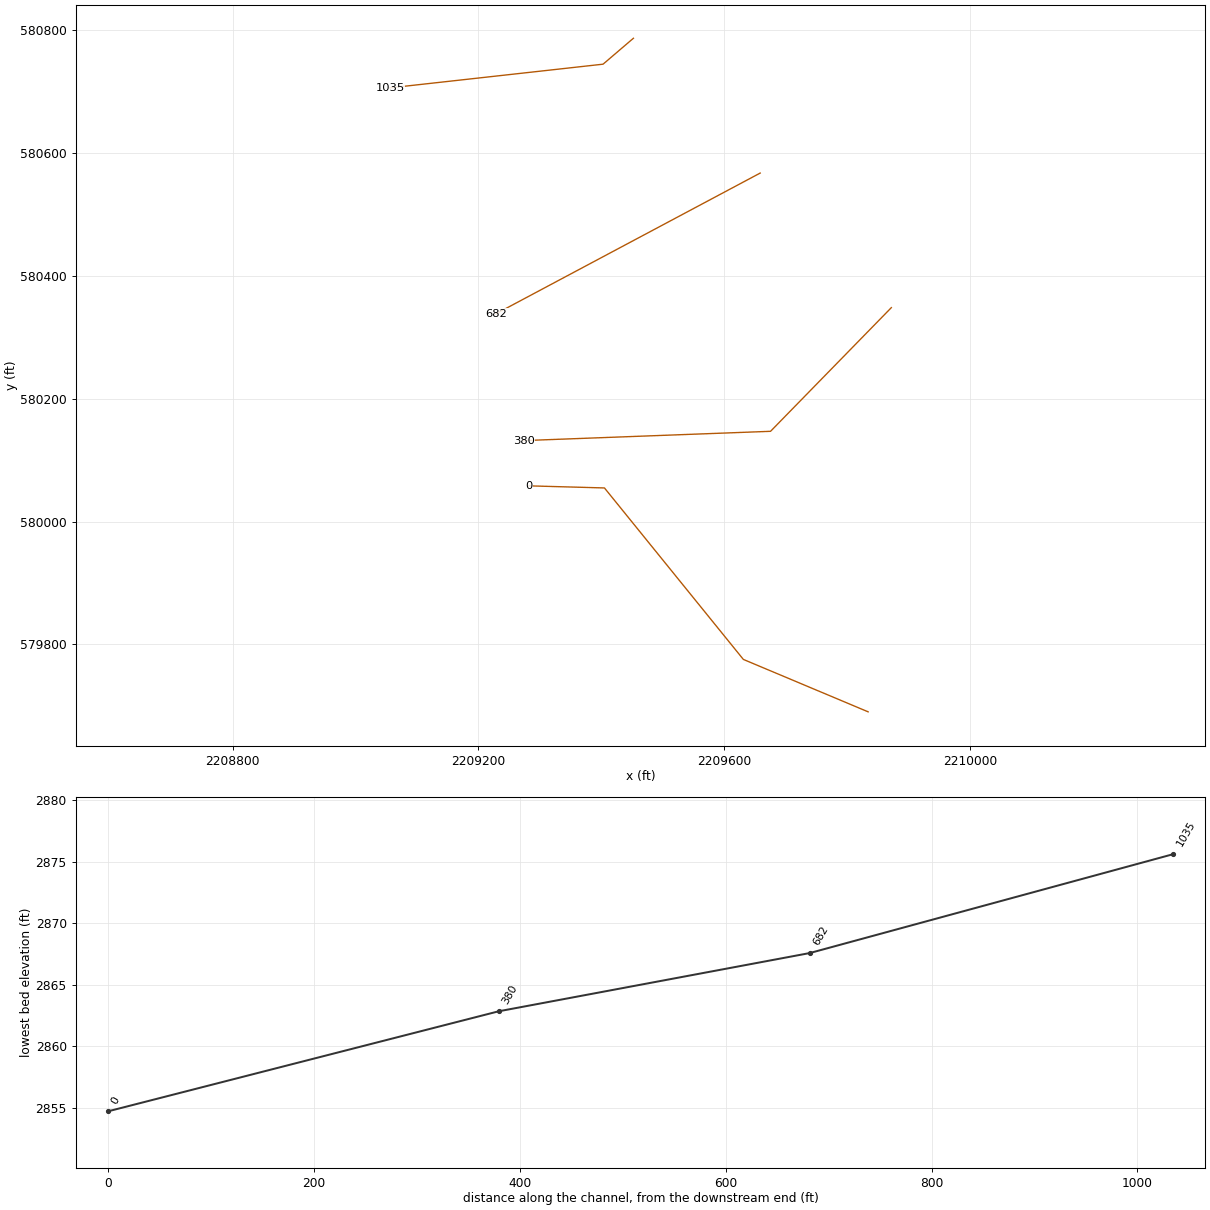
HEC-RAS study LFBFELKRV.prj: LFBFELKRV

--- LFBFELKRV.g01 (geometry) --- (continued)

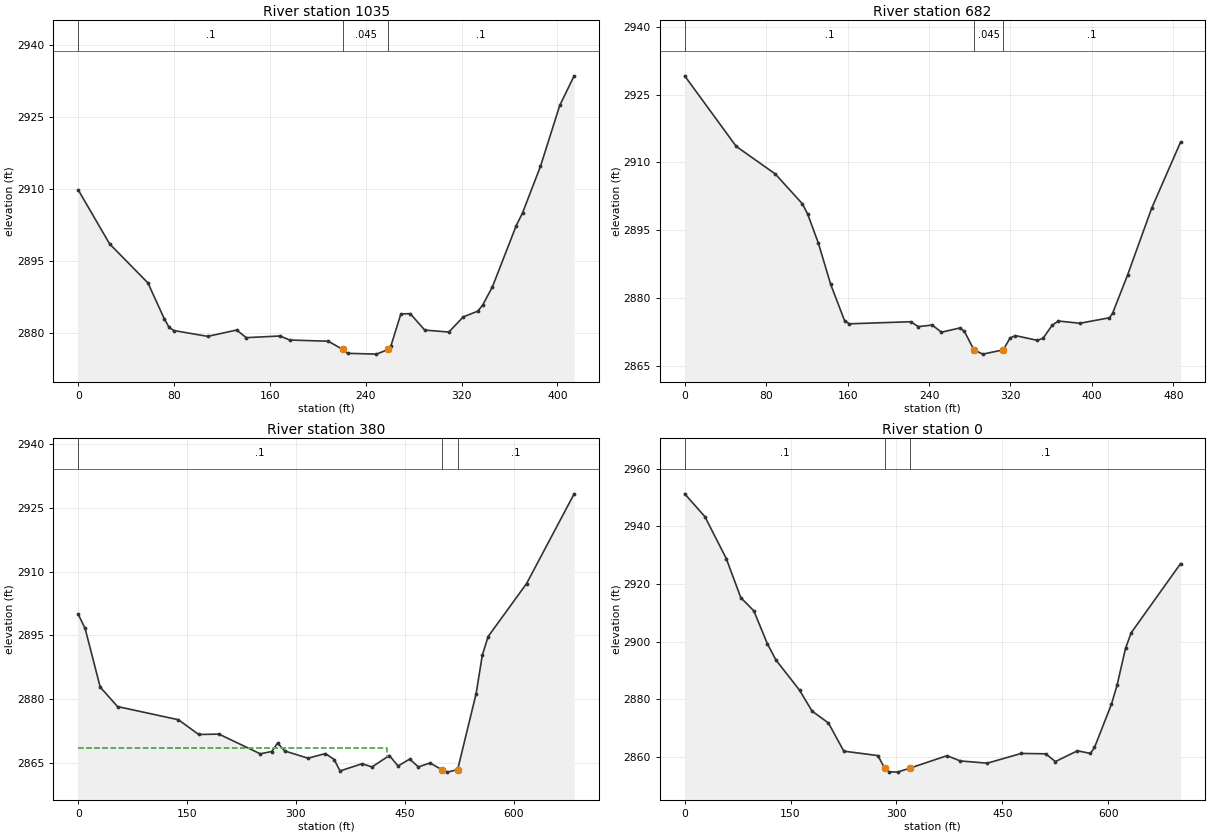
Type RM Length L Ch R = 1 ,1035    ,342.3,353.3,357.5
XS GIS Cut Line= 3
2209452.43553315580786.1884240992209403.05748153580744.036428813
2209056.20677747580705.497461695
#Sta/Elev= 30
       0 2909.83    26.2 2898.58    58.2 2890.44    71.8 2882.99    75.9 2881.16
    79.9 2880.52   108.1 2879.31   132.2 2880.63   140.3 2879.04   168.4 2879.39
   176.5 2878.55   208.7  2878.3   220.8 2876.58   224.8 2875.78   248.9 2875.61
  258.812876.592     261 2877.34   269.3    2884   277.1 2884.04   289.2 2880.62
   309.3 2880.21   321.4 2883.38   333.4 2884.55   337.5 2885.81   345.7 2889.64
   365.6  2902.4   370.8 2905.02   385.8 2914.74   401.9 2927.44   413.9 2933.59
#Mann= 3 ,-1,0
       0      .1       0   220.8    .045       0  258.81      .1       0
Bank Sta=220.8,258.81
XS Rating Curve= 0 ,0
Exp/Cntr(USF)=0,0
Exp/Cntr=0.3,0.1

Type RM Length L Ch R = 1 ,682     ,307.5,302.1,295.2
XS GIS Cut Line= 2
2209658.79062734580566.8851362062209228.84027542 580338.06001894
#Sta/Elev= 30
       0 2929.16    50.6 2913.55    89.1 2907.42   115.6 2900.84   120.8 2898.57
   131.3 2892.14   143.4 2883.01     157    2875   161.6 2874.28     222 2874.74
   229.5 2873.66   243.1 2874.01   252.2 2872.42   270.3 2873.36   274.8 2872.58
   284.1 2868.52   292.8 2867.57  312.86 2868.51   319.6 2871.14   324.7 2871.67
   346.2 2870.63   351.9 2871.06   360.9 2873.95   366.9  2874.9   388.1  2874.4
   417.2 2875.62   420.2 2876.57     435 2885.08   458.6 2899.82   487.1 2914.53
#Mann= 3 ,-1,0
       0      .1       0   284.1    .045       0  312.86      .1       0
Bank Sta=284.1,312.86
XS Rating Curve= 0 ,0
Exp/Cntr(USF)=0,0
Exp/Cntr=0.3,0.1

Type RM Length L Ch R = 1 ,380     ,398.9,379.6,359.1
XS GIS Cut Line= 3
 2209872.2633797580347.9537087552209675.64087346580146.742647169
2209273.63127241580131.643238424
#Sta/Elev= 30
       0 2899.98     9.5 2896.64    30.3 2882.85    54.2 2878.26   138.1 2875.16
   166.1 2871.69     194 2871.78   250.9 2867.15   266.7 2867.69   274.8 2869.66
   284.8 2867.81   316.8 2866.11   340.8 2867.21   352.8  2865.8   360.9 2863.12
   391.4 2864.82   404.9 2864.05   428.9 2866.75   440.9 2864.28   456.9 2865.91
   468.9 2864.07   484.9 2864.99     501 2863.44     509 2862.84  523.03 2863.45
   548.5 2881.32     557 2890.34     565 2894.72     618 2907.18   683.6 2928.29
#Mann= 3 ,-1,0
       0      .1       0     501    .045       0  523.03      .1       0
#XS Ineff= 2 , 0
           425.9 2868.45
Permanent Ineff=
       F       F
Bank Sta=501,523.03
XS Rating Curve= 0 ,0
Exp/Cntr(USF)=0,0
Exp/Cntr=0.3,0.1

Type RM Length L Ch R = 1 ,0       ,,,
XS GIS Cut Line= 4
2209834.50056629579690.3947807042209631.40429951579775.637117832
2209405.28231693580054.6196838912209282.18275873580058.022378714
#Sta/Elev= 30
       0 2951.33    28.6 2943.42    58.9 2928.87    79.5 2915.29      98 2910.69
     117 2899.36   129.2 2893.66   162.8 2883.13   180.4 2875.91   203.6 2871.79
   225.4    2862   273.7 2860.45  283.192856.135   289.1 2854.85   301.6 2854.71
  319.382856.132   371.5 2860.41   390.6 2858.59   428.7 2857.82   476.8  2861.2
   511.3 2861.07   525.1 2858.38   556.4 2862.12   574.8  2861.2   580.5 2863.27
   604.5 2878.27   612.5 2884.93   624.5 2897.71   632.5 2903.09   702.5 2927.13
#Mann= 3 ,-1,0
       0      .1       0  283.19    .045       0  319.38      .1       0
Bank Sta=283.19,319.38
XS Rating Curve= 0 ,0
Exp/Cntr=0.3,0.1
LCMann Table=0

Chan Stop Cuts=-1
Use User Specified Reach Order=0
Composite Channel Slope=5